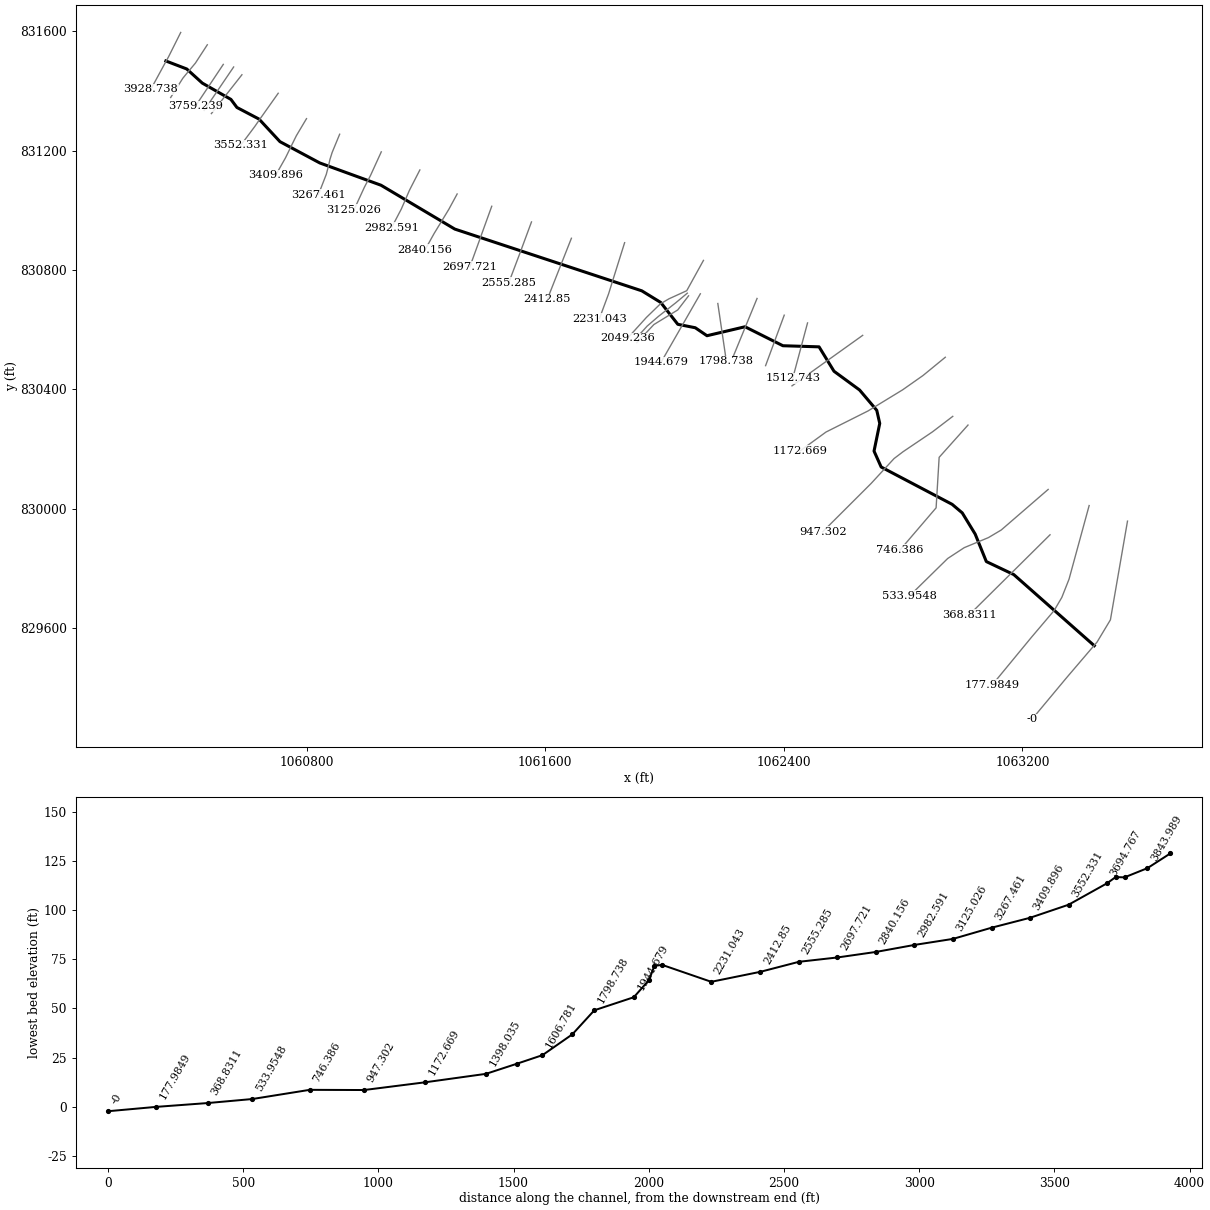
--- 20_ras.prj (project) ---

Proj Title=20
Current Plan=p01
Default Exp/Contr=0.3,0.1
English Units
Geom File=g01
Flow File=f01
Plan File=p01
Y Axis Title=Elevation
X Axis Title(PF)=Main Channel Distance
X Axis Title(XS)=Station
BEGIN DESCRIPTION:
RFD model 20 exported to HEC-RAS
END DESCRIPTION:

--- 20_ras.p01 (plan) ---

Plan Title=Plan 01
Program Version=4.10
Short Identifier=Plan 01
Geom File=g01
Flow File=f01
Subcritical Flow
Calc Critical at every XS
Secant Critical Depth

--- 20_ras.f01 (steady flow) ---

Flow Title=Flow 01
Program Version=5.01
Number of Profiles= 6
Profile Names=10yr,25yr,50yr,100yr,100plus,500yr
River Rch & RM=20,31,3928.738
   54.01  112.27  179.62  260.12  379.77  1017.3
River Rch & RM=20,31,2555.285
   54.46  113.21  181.14  262.33  383.01 1024.82
River Rch & RM=20,31, 2412.85
   67.93  141.48  226.71  328.64  479.82 1246.07
River Rch & RM=20,31,2231.043
   69.79  145.38  232.99  337.79  493.17 1276.06
River Rch & RM=20,31,2049.236
   71.63  149.25  239.24  346.88  506.45 1305.78
River Rch & RM=20,31,2020.738
   72.62  151.33  242.59  351.76  513.57 1321.67
River Rch & RM=20,31,1798.738
   74.45  155.17  248.78  360.78  526.73 1350.98
River Rch & RM=20,31,1717.257
   75.29  156.94  251.63  364.93  532.79 1364.43
River Rch & RM=20,31,1606.781
   75.99  158.41     254  368.38  537.83 1375.59
River Rch & RM=20,31,1512.743
   76.27  158.99  254.95  369.75  539.84 1380.05
River Rch & RM=20,31,1398.035
  117.15   245.2  394.37  573.14  836.78 2019.07
River Rch & RM=20,31,1172.669
  173.08   362.8  584.27  849.61 1240.44 2833.53
River Rch & RM=20,31, 947.302
  175.05  366.96  591.02  859.47 1254.82 2862.01
River Rch & RM=20,31, 746.386
  177.01  371.11  597.74  869.29 1269.16 2890.38
River Rch & RM=20,31,533.9548
  177.47  372.08  599.32  871.59 1272.52 2897.04
River Rch & RM=20,31,368.8311
  182.83  383.44  617.75  898.56 1311.89 2974.84
River Rch & RM=20,31,177.9849
  196.45  412.26   664.5  966.85 1411.61 3169.98
River Rch & RM=20,31,      -0
  196.67  412.73  665.27  967.98 1413.25 3173.19
Boundary for River Rch & Prof#=20,31,1
Up Type= 0
Dn Type= 2
Boundary for River Rch & Prof#=20,31,2
Up Type= 0
Dn Type= 2
Boundary for River Rch & Prof#=20,31,2
Up Type= 0
Dn Type= 2
Boundary for River Rch & Prof#=20,31,2
Up Type= 0
Dn Type= 2
Boundary for River Rch & Prof#=20,31,2
Up Type= 0
Dn Type= 2
Boundary for River Rch & Prof#=20,31,2
Up Type= 0
Dn Type= 2

--- 20_ras.g01 (geometry) ---

Geom Title=20
Program Version=4.10

River Reach=20,31
Reach XY= 30
1060328.15996446831500.6643929591060398.08368443831473.853141339
1060450.39088935831426.4079489941060546.22541596831371.836100279
1060566.33519823831344.8135803631060640.49002036831305.850877207
1060710.75942739 831230.093245521060844.10156585831158.798094358
1061049.59840343831084.0148415281061296.79155985830937.063471706
1061923.70786013830730.0462842871061987.14647968830691.117603334
 1062044.4567702830617.8106989421062103.02850827830606.277434568
1062142.26366561 830579.550152291062269.79349823830609.564607223
1062396.80737619830545.9840737731062518.01952119830542.258711314
1062568.12176487830460.413381649 1062653.8747936830397.596502652
1062711.47983794830329.4566074981062721.46718277830285.571676708
1062702.34370111830192.746185425 1062726.2819142830139.335204721
1062964.23639772830014.2210603151062998.09056439829985.575226973
1063041.49334217 829914.394671421063078.81973105829822.380782525
1063170.89360537829778.6911251741063440.79889772 829540.26272698

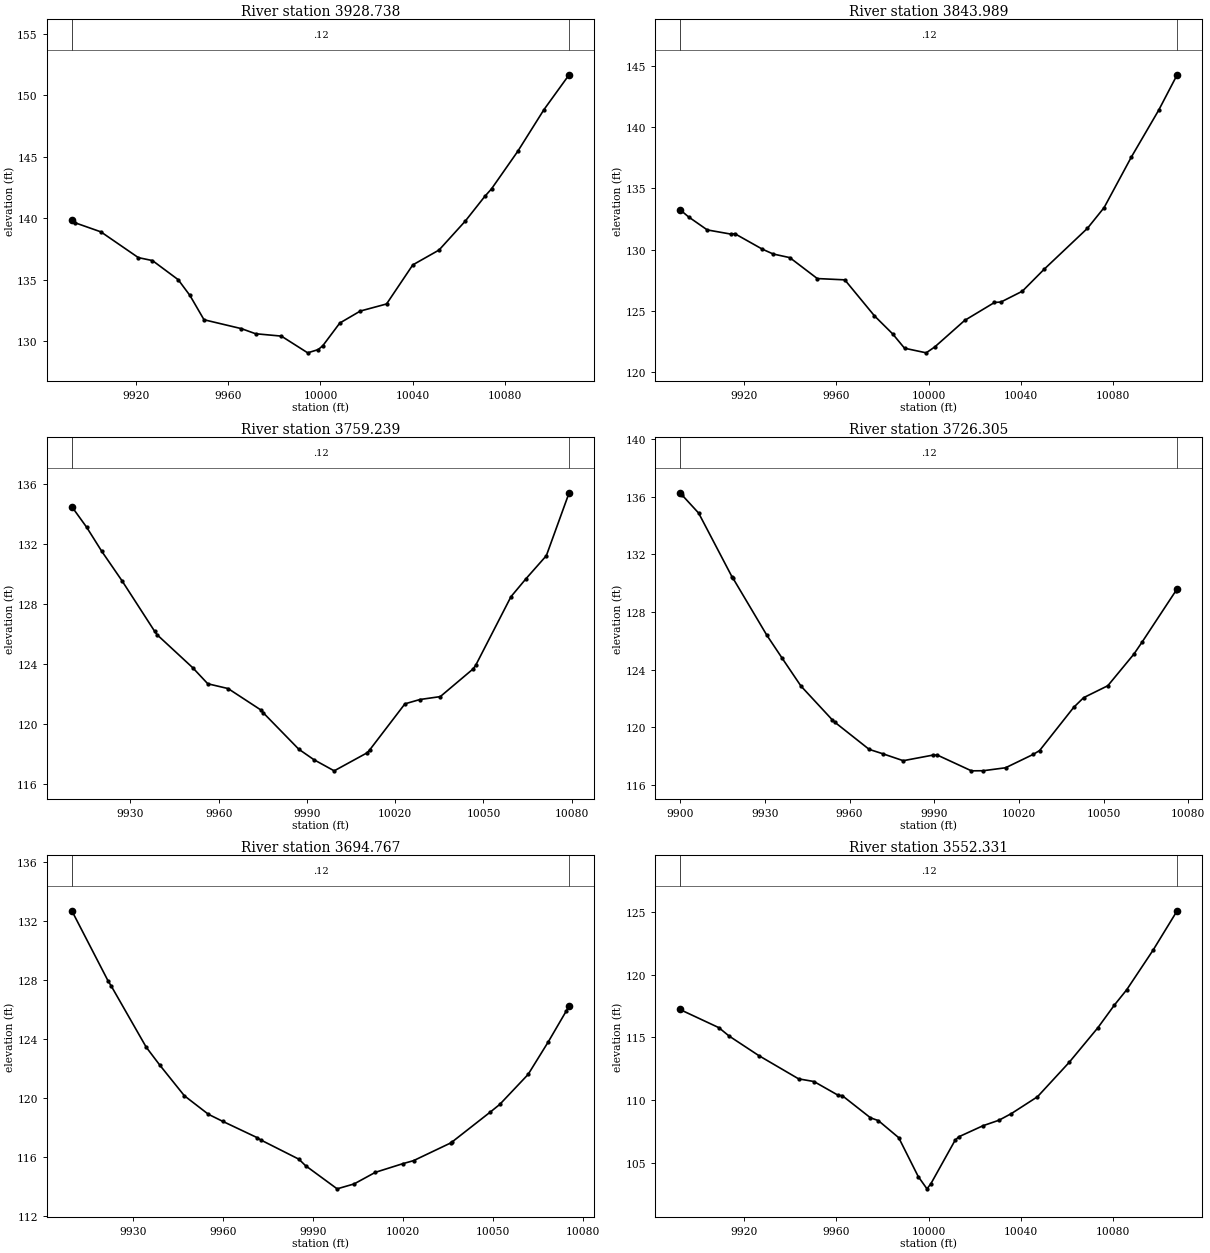
Type RM Length L Ch R = 1 ,3928.738,84.749500,84.749500,84.749500
XS GIS Cut Line= 5
1060377.90354671831596.2664242931060337.10709254831514.686097466
1060329.52761439831501.0243008341060328.51987234831499.296743033
1060277.52275682831405.419930289
#Sta/Elev= 25
9892.164139.8586 9893.58139.63429904.761138.89789921.014136.80279927.122136.5631
9938.303135.00649943.372133.72789949.483131.7515 9965.73131.02689971.845130.6143
9983.026130.42119994.453129.0608    9999 129.325   10001129.639810008.37131.4834
10017.27132.459510028.65133.034610040.03136.211710051.41137.420210062.79 139.773
10071.22141.773810074.17142.394810085.55145.447210096.93148.842710107.83151.6705
#Mann= 3 , 0 , 0
9892.164    0.12       09892.164    0.12       010107.83    0.12       0
#XS Ineff= 2 , 0
       0                               0
Bank Sta=9892.164,10107.83
Exp/Cntr=0.3,0.1

Type RM Length L Ch R = 1 ,3843.989,84.749500,84.749500,84.749500
XS GIS Cut Line= 6
1060467.05212545 831554.958331151060427.10179476831493.466476275
1060405.65140439831467.7887171631060404.24645916831466.365295614
  1060385.001827831442.8258102771060344.24225849831378.225193553
#Sta/Elev= 25
9892.212133.26989895.978132.67269904.087131.60539914.334131.26279916.012131.2992
9927.937 130.0349932.689129.63369939.863129.33859951.788127.62599963.713127.5196
9976.573124.57249984.418 123.1069989.604121.9256    9999121.547510002.76122.0378
10015.68124.2011 10028.6125.668510031.41 125.70610040.66126.587710050.15128.3909
10068.89131.736310076.13133.434210087.95137.574810099.78141.401710107.79144.3001
#Mann= 3 , 0 , 0
9892.212    0.12       09892.212    0.12       010107.79    0.12       0
#XS Ineff= 2 , 0
       0                               0
Bank Sta=9892.212,10107.79
Exp/Cntr=0.3,0.1

Type RM Length L Ch R = 1 ,3759.239,32.934300,32.934300,32.934300
XS GIS Cut Line= 2
1060520.62909812831489.1887388971060426.87909812831348.563738897
#Sta/Elev= 25
9910.096134.5013 9915.13133.12879920.244 131.5269927.149129.55239938.272126.1652
9939.167125.92859951.186123.7414  9956.3122.66959963.204  122.359974.327120.9205
9975.223120.71699987.241118.29479992.355117.5991 9999.26 116.85210010.38118.0484
10011.28118.2374 10023.3121.329110028.41121.617910035.32121.812510046.44123.6558
10047.33123.895310059.35128.491710064.47129.694210071.37131.230210079.11135.4324
#Mann= 3 , 0 , 0
9910.096    0.12       09910.096    0.12       010079.11    0.12       0
#XS Ineff= 2 , 0
       0                               0
Bank Sta=9910.096,10079.11
Exp/Cntr=0.3,0.1

Type RM Length L Ch R = 1 ,3726.305,31.538300,31.538300,31.538300
XS GIS Cut Line= 2
1060555.35132036831480.5081833451060456.39298701831334.674849987
#Sta/Elev= 27
9899.857136.26129900.483136.13779906.514134.85339918.292130.45399918.599130.3688
9930.684126.38969936.101124.80199942.768122.87029953.911120.52039954.853120.3503
9966.938118.4832 9971.72118.18199979.023 117.698 9989.53118.08469991.108 118.087
10003.19 116.99510007.34117.002310015.28117.207510025.15118.140810027.36118.4036
10039.45121.397610042.96 122.06610051.53122.892910060.77125.083810063.62125.9015
 10075.7129.4875 10076.1129.6188
#Mann= 3 , 0 , 0
9899.857    0.12       09899.857    0.12       0 10076.1    0.12       0
#XS Ineff= 2 , 0
       0                               0
Bank Sta=9899.857,10076.1
Exp/Cntr=0.3,0.1

Type RM Length L Ch R = 1 ,3694.767,142.435100,142.435100,142.435100
XS GIS Cut Line= 2
1060583.12909812831454.4665166591060480.69854259 831324.25818333
#Sta/Elev= 25
9909.621132.70179921.666127.95559922.769127.59189934.389123.45579938.943122.2302
9947.112120.15769955.116118.90229959.836118.4282 9971.29117.32489972.559117.1616
9985.282115.85459987.464  115.429998.006113.846810003.64114.178310010.73114.9658
10019.81115.548710023.45115.758210035.99116.973210036.18117.0073 10048.9119.0338
10052.16119.567810061.62121.603910068.33123.810110074.35  125.9110075.29126.2459
#Mann= 3 , 0 , 0
9909.621    0.12       09909.621    0.12       010075.29    0.12       0
#XS Ineff= 2 , 0
       0                               0
Bank Sta=9909.621,10075.29
Exp/Cntr=0.3,0.1

Type RM Length L Ch R = 1 ,3552.331,142.435100,142.435100,142.435100
XS GIS Cut Line= 5
1060704.77734952831392.438051212 1060643.0046201831305.272599137
1060641.83601064831303.6495304551060626.13256997831280.856947416
1060578.70361657831217.478727455
#Sta/Elev= 26
9892.165117.22849909.075115.77439913.538115.1023 9926.37113.54589943.665111.6837
9950.308111.47149960.959110.35749962.564110.34729974.821108.57419978.254 108.347
9987.078106.98369995.549103.87649999.336102.8962   10001103.2948 10011.5106.7663
10013.05107.047410023.65  107.9410030.57108.379810035.99108.915210047.26110.2534
10060.97112.993810073.46115.769710080.64117.584610085.95118.800310097.33 121.948
10107.84125.1133
#Mann= 3 , 0 , 0
9892.165    0.12       09892.165    0.12       010107.84    0.12       0
#XS Ineff= 2 , 0
       0                               0
Bank Sta=9892.165,10107.84
Exp/Cntr=0.3,0.1

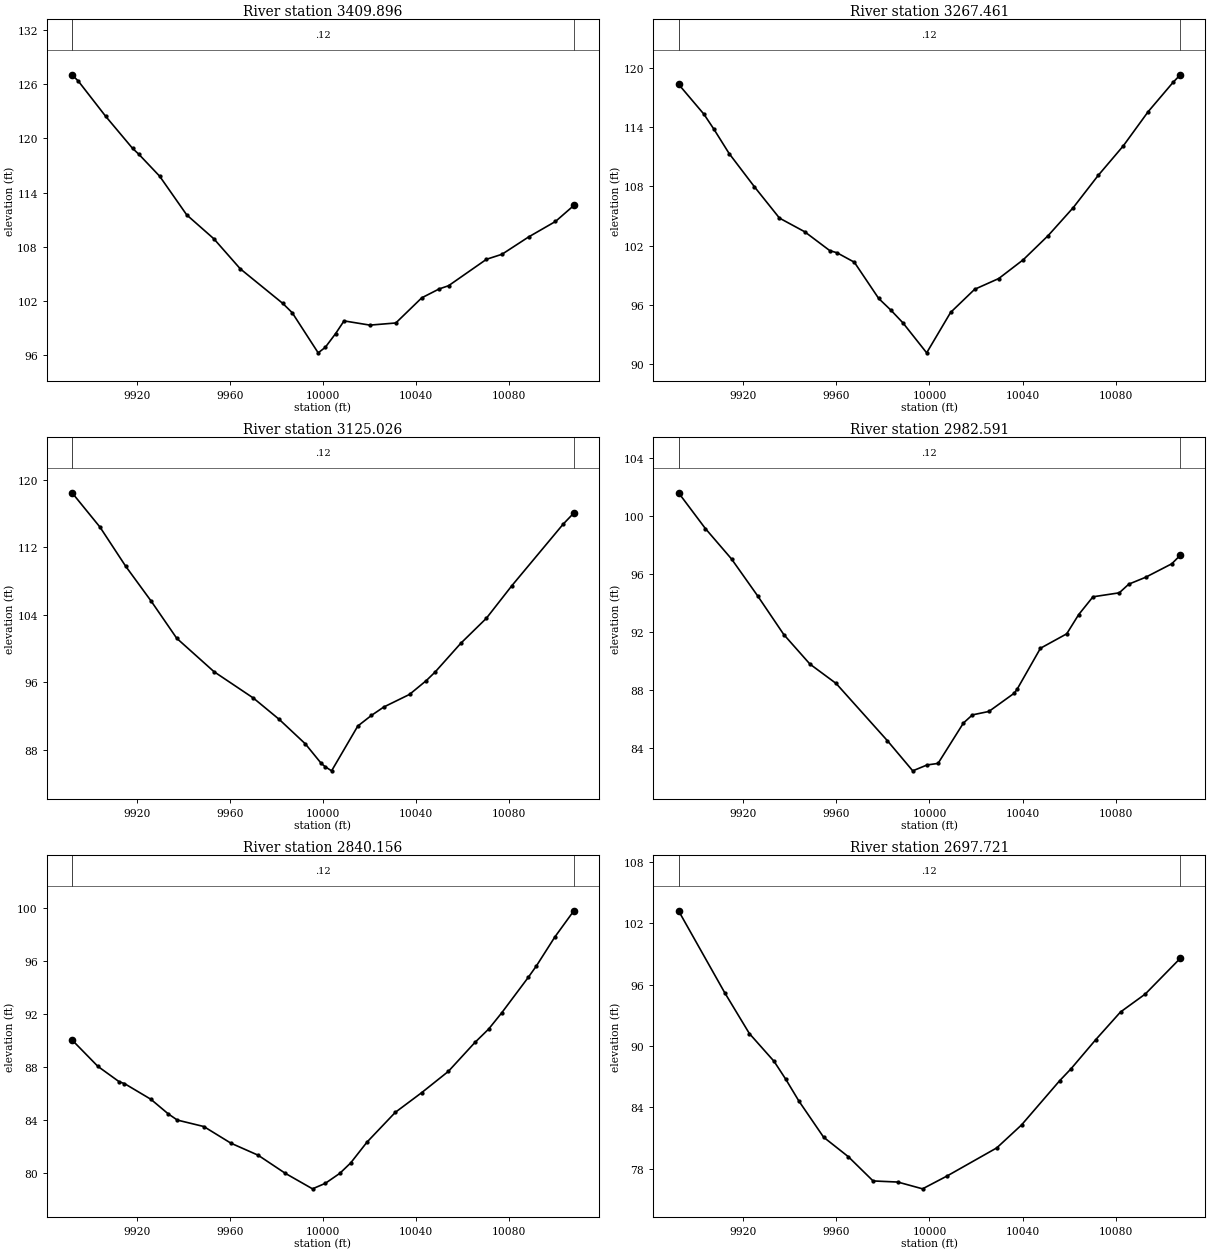
Type RM Length L Ch R = 1 ,3409.896,142.435200,142.435200,142.435200
XS GIS Cut Line= 6
1060799.65499252831307.3532390081060765.75837577831250.365531679
 1060747.7797426831214.0543889711060746.93942236831212.239489004
1060729.17340371831175.8517320421060696.51110959 831118.11309881
#Sta/Elev= 25
9892.175127.04239894.913126.32519906.548122.46389918.184118.88759920.842118.2465
9929.819115.80579941.454111.52039953.089108.87919964.469105.54619982.728 101.717
9986.786100.68599997.945 96.2399   1000196.8492810005.4298.3656310009.0699.77847
10020.1899.3100510031.3199.5482510042.47102.336610049.97 103.32210053.96103.6723
10070.28106.603510076.94 107.15810088.43109.084710099.92 110.79110107.83112.5663
#Mann= 3 , 0 , 0
9892.175    0.12       09892.175    0.12       010107.83    0.12       0
#XS Ineff= 2 , 0
       0                               0
Bank Sta=9892.175,10107.83
Exp/Cntr=0.3,0.1

Type RM Length L Ch R = 1 ,3267.461,142.435100,142.435100,142.435100
XS GIS Cut Line= 6
1060910.79445416831255.1018365351060885.53360637831193.805229504
1060878.07762777831170.052980498 1060874.3675563831152.832177753
1060865.91844327831120.4493879281060839.33301277831052.119286751
#Sta/Elev= 25
9892.189118.31219903.115115.28089907.396113.7684 9913.93111.31249924.746 107.967
9935.562104.78729946.378103.41179957.194101.49989960.268101.28719967.715 100.334
9978.19696.667569983.38195.501019988.55794.218579998.80191.1768410009.0995.26132
10019.4397.5978810029.7698.6815510040.31100.583410051.04103.030210061.77105.8442
 10072.5109.100510083.24112.070910093.97  115.54 10104.7118.509810107.79119.2671
#Mann= 3 , 0 , 0
9892.189    0.12       09892.189    0.12       010107.79    0.12       0
#XS Ineff= 2 , 0
       0                               0
Bank Sta=9892.189,10107.79
Exp/Cntr=0.3,0.1

Type RM Length L Ch R = 1 ,3125.026,142.435100,142.435100,142.435100
XS GIS Cut Line= 6
1061050.31147127831195.9390135781061014.62068699831117.645851797
1061005.13040597831099.1477053971061004.14238715831097.408792282
 1060993.6082656831077.1083169681060958.46568038831000.851967729
#Sta/Elev= 23
9892.165118.43619904.187114.35949915.177109.74389926.167105.59519937.157101.1919
9953.18797.233159970.12794.103549981.183  91.5879992.42288.684129999.26486.36852
   1000185.9679610003.7185.4862410014.98 90.797210020.8592.0571710026.1993.05552
 10037.294.5413210044.4496.1865910048.2197.1950210059.22100.594810070.24103.5671
10081.25107.446510103.27114.727410107.84116.0405
#Mann= 3 , 0 , 0
9892.165    0.12       09892.165    0.12       010107.84    0.12       0
#XS Ineff= 2 , 0
       0                               0
Bank Sta=9892.165,10107.84
Exp/Cntr=0.3,0.1

Type RM Length L Ch R = 1 ,2982.591,142.435100,142.435100,142.435100
XS GIS Cut Line= 6
1061179.65884478831135.2659775261061144.82140062831067.283930043
1061132.75504973831039.3357348421061132.02374498831037.474231855
1061117.21333686831003.7518606331061084.72394001830941.753775397
#Sta/Elev= 25
 9892.17101.57559903.70599.109899914.94297.013719926.17894.467229937.41591.80112
9948.65189.765299959.888 88.43279981.93884.48444 9992.8382.40803    9999 82.8142
 10003.782.9194710014.6285.7059110018.4786.2648410025.5586.5012510036.4787.76247
10037.8388.0736710047.7190.85783   1005991.8529110064.1493.1778910070.2994.40516
10081.5894.6789810085.6995.2774310092.8795.7482710104.1696.6815810107.8397.27238
#Mann= 3 , 0 , 0
 9892.17    0.12       0 9892.17    0.12       010107.83    0.12       0
#XS Ineff= 2 , 0
       0                               0
Bank Sta=9892.17,10107.83
Exp/Cntr=0.3,0.1

Type RM Length L Ch R = 1 ,2840.156,142.435200,142.435200,142.435200
XS GIS Cut Line= 6
1061304.68808545831054.7677378981061277.13957228831003.956006437
1061251.73009461830962.0188113571061250.67845042830960.317622218
1061227.47125809830922.2568386351061197.18791068830867.861001671
#Sta/Elev= 26
9892.16690.055139903.27788.064079912.49386.898519914.65386.772919926.02885.58671
9933.47484.490319937.40384.018389948.77883.531819960.437 82.2762 9972.1381.36971
9983.82280.003259995.51478.83393   1000179.2480210007.2380.0001710011.9180.78618
10018.9482.3584910031.1284.6040810042.3786.0765110053.8887.6858810065.3389.87235
10071.2290.8804810076.7792.0885310088.22 94.770710091.7895.6494610099.6697.81911
10107.8499.79641
#Mann= 3 , 0 , 0
9892.166    0.12       09892.166    0.12       010107.84    0.12       0
#XS Ineff= 2 , 0
       0                               0
Bank Sta=9892.166,10107.84
Exp/Cntr=0.3,0.1

Type RM Length L Ch R = 1 ,2697.721,142.435100,142.435100,142.435100
XS GIS Cut Line= 4
1061420.68419168831013.6352219821061384.36795657830913.163757666
1061383.74949431830911.2617838421061347.33236303830810.827239261
#Sta/Elev= 20
9892.167103.23869911.982 95.23069922.61591.220329933.24888.493739938.306 86.7283
9943.88184.618869954.51581.075189965.14879.163599975.78176.791769986.41476.68302
9997.04776.0188810007.6677.2869510028.93  80.02710039.5782.27034   1005686.61152
10060.8587.7700810071.48 90.623110082.1293.3301310092.7695.0878610107.83 98.5904
#Mann= 3 , 0 , 0
9892.167    0.12       09892.167    0.12       010107.83    0.12       0
#XS Ineff= 2 , 0
       0                               0
Bank Sta=9892.167,10107.83
Exp/Cntr=0.3,0.1

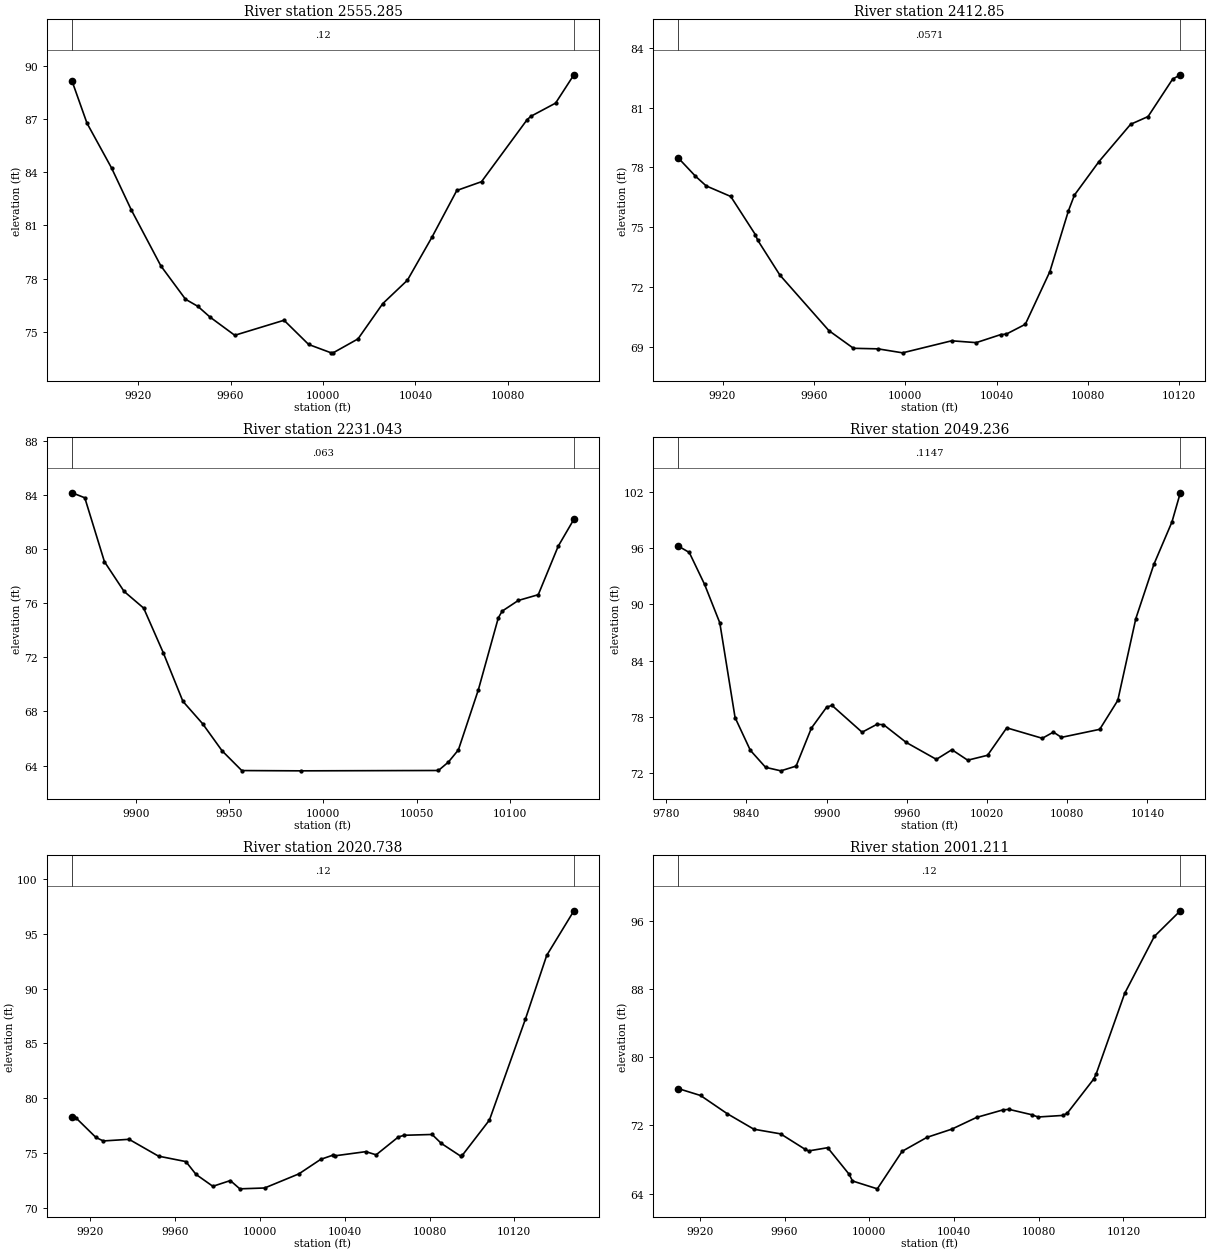
Type RM Length L Ch R = 1 ,2555.285,142.435100,142.435100,142.435100
XS GIS Cut Line= 4
1061553.89293249830961.047162753 1061516.5709621830860.121635246
1061515.89583428830858.2390300241061477.83620543830757.589592194
#Sta/Elev= 23
9891.39589.141559897.84286.771949908.504 84.23699917.03581.873589929.82878.71601
 9940.4976.834069945.86676.430099951.15175.821319961.81374.799259983.137 75.6475
9993.79974.2804310003.5373.8086610004.4673.8137510015.1574.5950910025.8576.58418
10036.5477.9072710047.2380.3500810057.9282.9723410068.6183.4669510088.3586.96645
10089.9987.1583110100.6887.9021110108.6189.50085
#Mann= 3 , 0 , 0
9891.395    0.12       09891.395    0.12       010108.61    0.12       0
#XS Ineff= 2 , 0
       0                               0
Bank Sta=9891.395,10108.61
Exp/Cntr=0.3,0.1

Type RM Length L Ch R = 1 , 2412.85,181.807200,181.807200,181.807200
XS GIS Cut Line= 2
1061687.72979257830906.2894333451061607.00062588830701.862350002
#Sta/Elev= 24
9900.69778.466169908.12977.563129912.83577.075269923.58776.546339934.33874.63824
9935.355  74.361 9945.09 72.60739966.59369.817779977.34468.933459988.09668.90563
9998.84768.7058210020.3569.30973 10031.169.2174210041.8569.6208110044.2669.64378
 10052.670.1365210063.3672.7804810071.4875.8242110074.1176.6139110084.8678.29611
10098.7180.1635410106.36 80.552410117.1182.4277510120.4982.64705
#Mann= 3 , 0 , 0
9900.697  0.0571       09900.697  0.0571       010120.49  0.0571       0
#XS Ineff= 2 , 0
       0                               0
Bank Sta=9900.697,10120.49
Exp/Cntr=0.3,0.1

Type RM Length L Ch R = 1 ,2231.043,181.807200,181.807200,181.807200
XS GIS Cut Line= 5
1061866.14496007 830891.486629041061826.23428574830764.559240793
1061825.68087919830762.6373299741061812.45055745830720.069441426
1061781.64976196830637.137471523
#Sta/Elev= 21
9865.94684.161489872.74683.790569883.22879.069239893.71176.873939904.19475.63564
9914.676 72.33459925.159 68.74449935.64267.097679946.12465.081829956.60763.62797
9988.05563.6073510061.6563.6329810066.9864.2543110072.3265.1543110082.9969.59855
10093.6574.91579 10095.775.4120210104.3276.2007810114.9976.6271210125.6680.21585
10134.0482.20549
#Mann= 3 , 0 , 0
9865.946   0.063       09865.946   0.063       010134.04   0.063       0
#XS Ineff= 2 , 0
       0                               0
Bank Sta=9865.946,10134.04
Exp/Cntr=0.3,0.1

Type RM Length L Ch R = 1 ,2049.236,28.498300,28.498300,28.498300
XS GIS Cut Line= 6
1062130.43812591 830832.070683331062074.44854257830730.508183345
1062014.55270925 830703.164433331061985.90687594830686.237350002
1061939.03187594 830640.664433331061875.22979257 830570.35193333
#Sta/Elev= 30
9789.16496.185879797.23895.519439808.65792.126549820.07688.017729831.495 77.9215
9842.91374.431729854.33272.613879865.75172.24092 9877.17 72.74759888.589 76.7936
9900.00879.031669903.995 79.21719926.516 76.35779937.50977.19146 9942.4877.17124
9959.49575.272429982.07573.46407 9993.6974.4936210005.5273.3755710020.3773.89876
10034.7276.8246510061.3175.7102810069.6376.3685310075.6375.8092910104.2876.66552
10117.7979.7487410131.2988.4738610144.79 94.2524 10158.398.7676210164.57101.8806
#Mann= 3 , 0 , 0
9789.164  0.1147       09789.164  0.1147       010164.57  0.1147       0
#XS Ineff= 2 , 0
       09906.521                       0
Bank Sta=9789.164,10164.57
Exp/Cntr=0.3,0.1

Type RM Length L Ch R = 1 ,2020.738,19.526500,19.526500,19.526500
XS GIS Cut Line= 5
1062076.31820068830722.2115754191062038.45762375830690.661094651
  1061979.563393830644.3870562021061941.70281607830611.784892738
1061899.63550839830565.510854289
#Sta/Elev= 28
9911.42678.281469913.14278.217079922.69176.405889926.15976.089359938.31276.23792
9952.19374.701429965.10774.205639969.87373.035949977.82471.948959986.05972.47288
9990.54271.7178510002.2471.7953410018.4373.0872610028.6974.4091710034.62 74.8044
10035.6174.7378810049.9975.1129810054.8374.8217310065.3276.4535210068.0276.60662
10081.22 76.680310085.5775.8645910094.7474.6972410095.5474.7960610108.2677.99442
10125.2787.2331110135.2893.0257210148.1197.09806
#Mann= 3 , 0 , 0
9911.426    0.12       09911.426    0.12       010148.11    0.12       0
#XS Ineff= 2 , 0
       0                               0
Bank Sta=9911.426,10148.11
Exp/Cntr=0.3,0.1

Type RM Length L Ch R = 1 ,2001.211,56.532600,56.532600,56.532600
XS GIS Cut Line= 4
1062080.52493149830713.272272542 1062044.2418786830665.946551383
1061964.31399396830617.0433061871061906.99728724830556.045710042
#Sta/Elev= 26
9909.87276.332149920.29675.527889932.89773.388969945.49771.562019958.09871.01789
9969.50669.22815 9971.32 69.00919980.34169.38858 9990.4866.263659992.06465.47747
10003.7964.5525910015.5168.9628910027.2370.6056610038.9671.5709810050.6872.95124
10063.2173.8399710066.0173.8956310076.8173.2616110079.7372.9992710091.4173.18405
10093.4673.4290110106.0277.4658910107.1878.0756610120.6287.5275710134.6294.22584
10146.9197.24607
#Mann= 3 , 0 , 0
9909.872    0.12       09909.872    0.12       010146.91    0.12       0
#XS Ineff= 2 , 0
       0                               0
Bank Sta=9909.872,10146.91
Exp/Cntr=0.3,0.1

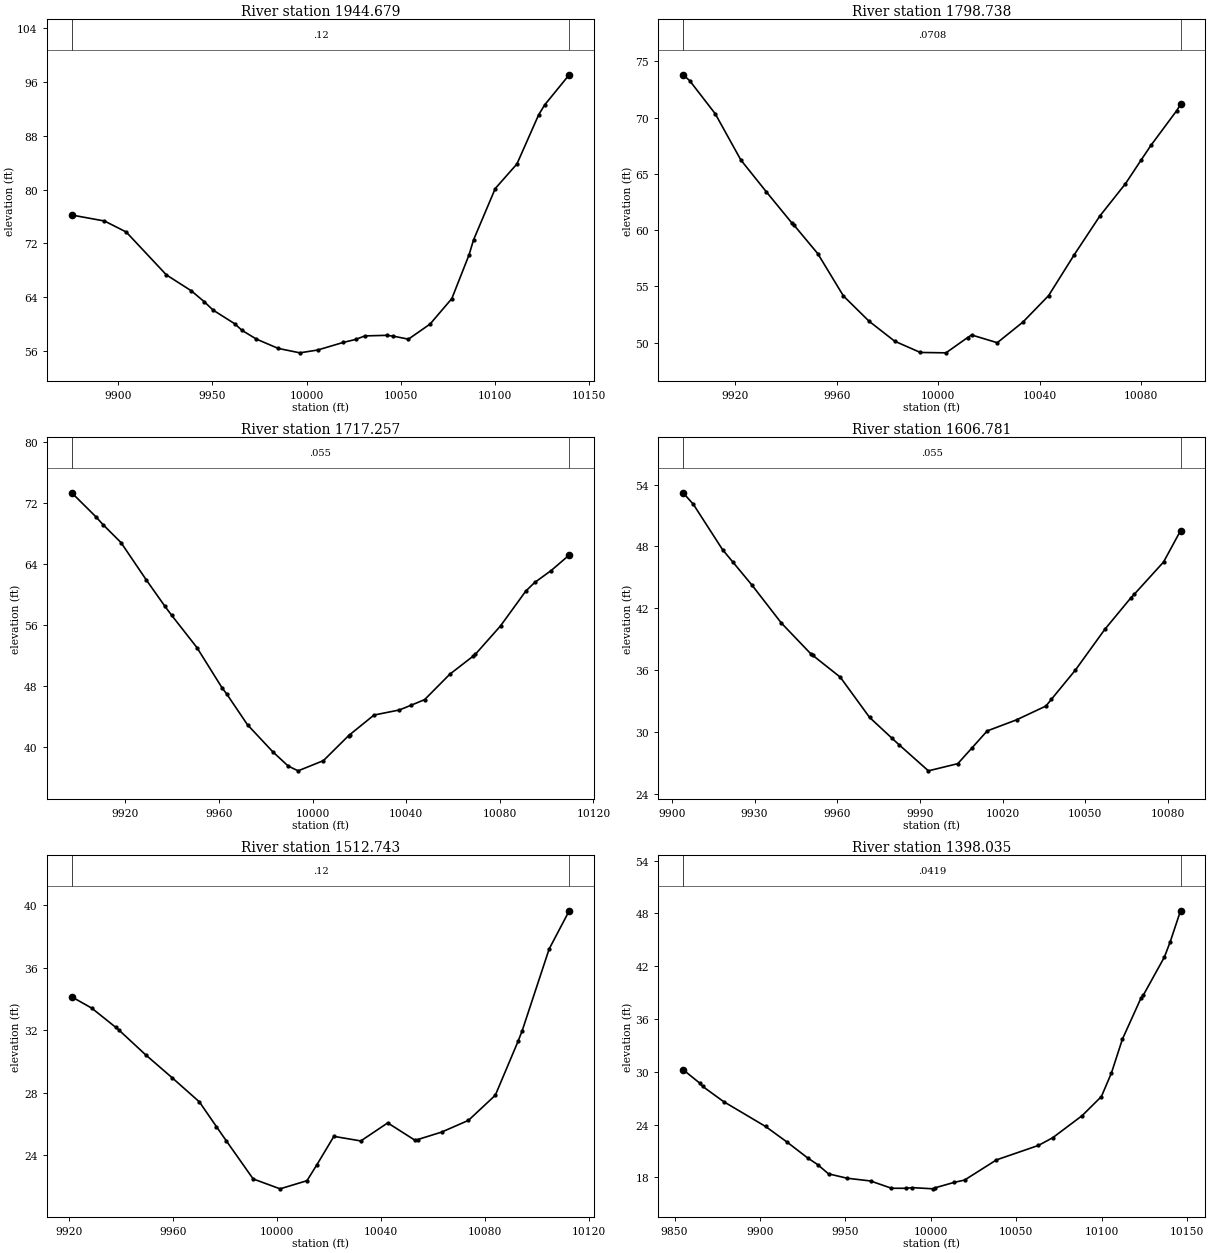
Type RM Length L Ch R = 1 ,1944.679,145.941000,145.941000,145.941000
XS GIS Cut Line= 2
1062120.02145922830720.0915166741061988.51104259830490.924849987
#Sta/Elev= 28
9875.306 76.22969892.70675.341299904.23573.707119925.57767.332269938.82464.96415
9945.66863.349199950.35462.105099961.88360.065229965.75959.082779973.41357.78507
9984.94256.406469996.47255.7452310005.9456.1648810019.5357.2945610026.0357.73081
10031.0658.2625510042.5958.3479410046.1258.2246910054.1257.7765510065.6560.02609
10077.1863.8092310086.31  70.29710088.7172.5306810100.24 80.166710111.77 83.8248
 10123.391.1310110126.4992.5956410139.5397.07591
#Mann= 3 , 0 , 0
9875.306    0.12       09875.306    0.12       010139.53    0.12       0
#XS Ineff= 2 , 0
       0                               0
Bank Sta=9875.306,10139.53
Exp/Cntr=0.3,0.1

Type RM Length L Ch R = 1 ,1798.738,81.480500,81.480500,81.480500
XS GIS Cut Line= 2
1062178.61520922 830687.539433331062207.26104259830493.529016674
#Sta/Elev= 25
9899.45673.808359902.02373.297449912.13270.34733 9922.24 66.23499932.34963.38578
9942.45760.603419943.16860.448199952.56557.906999962.674 54.14519972.78251.89924
9982.89150.121089992.99949.1205110003.1149.0868510011.6350.4462110013.2250.67532
10023.3249.9866710033.43 51.820610043.5454.1689610053.65 57.802710063.7661.25189
10073.8764.1282210080.0966.2479610083.97 67.554510094.0870.6271510095.5771.17064
#Mann= 3 , 0 , 0
9899.456  0.0708       09899.456  0.0708       010095.57  0.0708       0
#XS Ineff= 2 , 0
       0                               0
Bank Sta=9899.456,10095.57
Exp/Cntr=0.3,0.1

Type RM Length L Ch R = 1 ,1717.257,110.476500,110.476500,110.476500
XS GIS Cut Line= 2
1062310.12562594830704.4665166741062229.39645922 830507.85193333
#Sta/Elev= 29
9897.11973.332319907.35270.208669910.61469.109459918.16366.797559928.97361.88865
9936.94258.420979939.78357.253729950.593 53.00939961.40347.687569963.269 46.9355
9972.21342.863919983.023 39.31299989.59737.443619993.83336.8136910004.6438.15305
10015.4541.4484110015.9341.5691610026.2644.1399410037.0744.8065510042.2545.44792
10047.8846.1658410058.6949.5161810068.5851.86685 10069.552.0982310080.3155.84773
10091.1260.4270910094.9161.5523410101.9363.1147810109.6665.15756
#Mann= 3 , 0 , 0
9897.119   0.055       09897.119   0.055       010109.66   0.055       0
#XS Ineff= 2 , 0
       0                               0
Bank Sta=9897.119,10109.66
Exp/Cntr=0.3,0.1

Type RM Length L Ch R = 1 ,1606.781,94.037800,94.037800,94.037800
XS GIS Cut Line= 2
1062401.27145922 830648.476933331062338.77145922830479.206100002
#Sta/Elev= 25
9904.08153.202589907.787 52.09659918.44747.667529922.18746.465969929.10744.23144
9939.76740.549219950.42637.567389951.05737.436579961.086 35.30859971.74631.39378
9979.92829.357149982.40628.747769993.06626.2097110003.7326.90676 10008.828.41281
10014.3930.0842910025.0531.1624210035.7132.5021410037.6733.1516210046.37 35.9871
10057.0339.9364610066.5443.0176110067.6943.3368210078.3546.4787110084.5249.51971
#Mann= 3 , 0 , 0
9904.081   0.055       09904.081   0.055       010084.52   0.055       0
#XS Ineff= 2 , 0
       0                               0
Bank Sta=9904.081,10084.52
Exp/Cntr=0.3,0.1

Type RM Length L Ch R = 1 ,1512.743,114.707300,114.707300,114.707300
XS GIS Cut Line= 2
1062479.39645922830622.4352666591062429.91729259 830437.53943333
#Sta/Elev= 25
 9920.9734.136989928.66733.416549937.97732.178239939.01832.03108 9949.3730.43549
9959.72228.946929970.07427.42199 9976.6625.832389980.42624.932969990.77822.49176
10001.1321.8592710011.4822.3801510015.3423.4136610021.8325.2152310032.1924.92213
10042.5426.0765710052.8924.9816610054.0325.0091310063.2425.4860810073.59 26.2367
10083.9427.8462110092.7131.30255 10094.331.9823910104.6537.1990910112.3739.64118
#Mann= 3 , 0 , 0
 9920.97    0.12       0 9920.97    0.12       010112.37    0.12       0
#XS Ineff= 2 , 0
       0                               0
Bank Sta=9920.97,10112.37
Exp/Cntr=0.3,0.1

Type RM Length L Ch R = 1 ,1398.035,225.366700,225.366700,225.366700
XS GIS Cut Line= 2
1062664.29229259830580.7686000021062427.31312588830411.497766674
#Sta/Elev= 30
9854.99730.234289864.921  28.6789866.41628.338849878.70526.605859903.28323.77809
9915.57222.046559927.86120.21099 9933.7419.44847 9940.1518.392619950.94517.89625
9964.72817.581519977.01716.753169985.35416.748749989.30616.82322 10001.6 16.6868
10002.56 16.805610013.8817.4313210019.7617.6793910038.4619.9771210063.0421.62115
10071.3822.4944610088.5825.0009810099.9127.1806110105.7929.87069 10112.233.70496
10122.9938.3365110124.4938.7230110136.7743.03029 10140.244.7824310146.2248.29302
#Mann= 3 , 0 , 0
9854.997  0.0419       09854.997  0.0419       010146.22  0.0419       0
#XS Ineff= 2 , 0
       0                               0
Bank Sta=9854.997,10146.22
Exp/Cntr=0.3,0.1

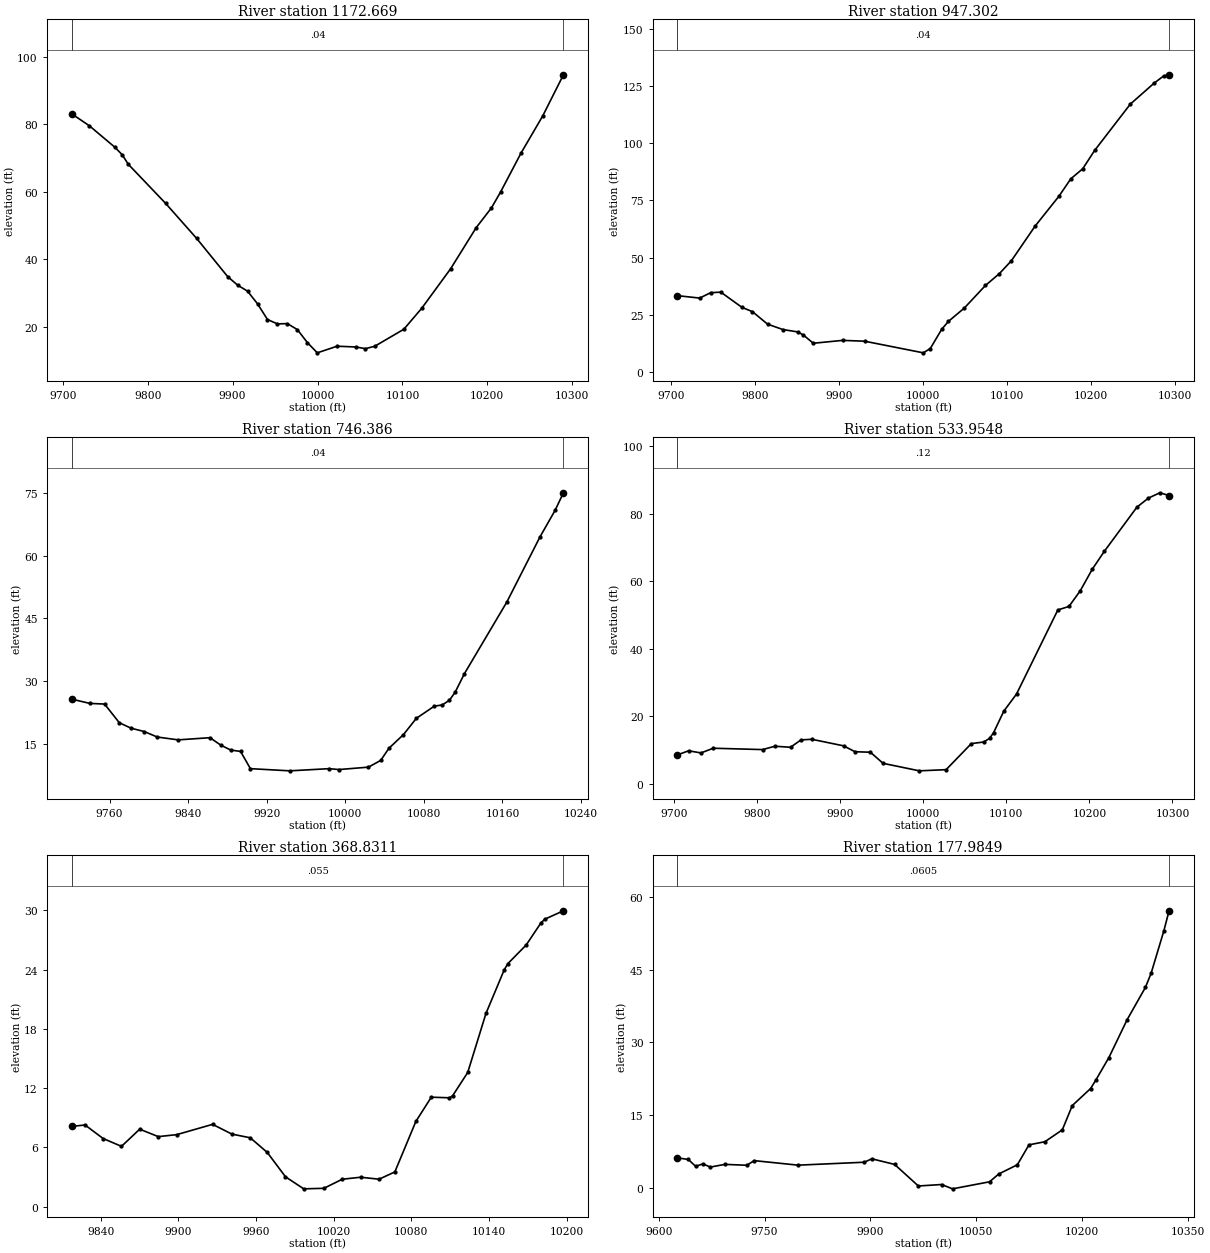
Type RM Length L Ch R = 1 ,1172.669,225.366800,225.366800,225.366800
XS GIS Cut Line= 6
1062941.25948203830507.348885038 1062866.6313409830446.213313623
1062798.49939376830398.3482012821062682.30855017830327.391281958
1062541.25784608 830256.614339371062455.91478991830194.465027052
#Sta/Elev= 30
9710.27883.097479731.29679.520269761.32473.178229770.07870.914569777.104 68.1449
9820.96556.609849857.62846.216689894.12234.929419905.85932.404929917.59630.60648
9929.33326.87152 9941.0722.226519952.80720.934999964.54421.012549976.28119.24093
9988.018 15.41879999.74712.3708510023.0314.3305910045.3214.1050410056.3913.60617
10067.4614.3210510101.6919.3480310122.8125.5602210156.92 37.278310186.9449.40346
10204.8755.2298710215.6759.9516410239.8171.4833310265.3482.45459 10289.794.61793
#Mann= 3 , 0 , 0
9710.278    0.04       09710.278    0.04       0 10289.7    0.04       0
#XS Ineff= 2 , 0
       0                               0
Bank Sta=9710.278,10289.7
Exp/Cntr=0.3,0.1

Type RM Length L Ch R = 1 , 947.302,200.916000,200.916000,200.916000
XS GIS Cut Line= 6
1062966.26673846830309.1581291541062898.37461768830257.314422842
1062799.54473751830190.5640689511062769.44317937 830167.67781375
1062692.56188017830084.254866416 1062530.4056881829922.442020213
#Sta/Elev= 30
9707.47933.413339734.23832.353759747.28534.711799759.40234.934419784.566 28.2787
9797.03826.410569814.90420.974199833.17618.614059850.63717.581229857.31116.29343
9869.37812.617379904.23713.878189930.43413.5175310000.218.43600610008.5310.30914
10022.0118.6633310030.0222.1541210048.9827.9850810074.1537.8739410090.73 43.0391
10104.8948.61215 10133.263.7855110161.5276.8149810175.6784.4409810189.83 88.8183
10203.9996.8173810246.46117.057810274.77126.226310286.06129.342510292.55129.8767
#Mann= 3 , 0 , 0
9707.479    0.04       09707.479    0.04       010292.55    0.04       0
#XS Ineff= 2 , 0
       0                               0
Bank Sta=9707.479,10292.55
Exp/Cntr=0.3,0.1

Type RM Length L Ch R = 1 , 746.386,212.431200,212.431200,212.431200
XS GIS Cut Line= 4
1063017.38806355830280.0727498231062920.62940788830171.855832309
1062910.44428623830002.5281848911062789.49596661829861.209621996
#Sta/Elev= 30
9721.26225.690289739.84824.664489754.85124.508739769.85320.050029781.72418.74283
9795.13917.939669808.553 16.62099829.86515.94226 9862.2116.464619873.29614.66121
9883.31413.509619893.332 13.1755 9903.359.0580189943.423 8.535999983.4959.056955
9993.513 8.8463110023.579.42033910036.0611.0402810044.4313.9474910059.1317.18569
 10072.3 21.091410090.5724.0038510098.6224.2961810105.95 25.403710111.7827.32927
10121.3331.8061710164.4348.9067510198.2364.5046410213.6170.8501210222.0775.04087
#Mann= 3 , 0 , 0
9721.262    0.04       09721.262    0.04       010222.07    0.04       0
#XS Ineff= 2 , 0
       0                               0
Bank Sta=9721.262,10222.07
Exp/Cntr=0.3,0.1

Type RM Length L Ch R = 1 ,533.9548,165.123700,165.123700,165.123700
XS GIS Cut Line= 6
1063286.14676013830064.2333405361063128.79398704829928.210790622
1063085.82386016829902.6942382391063004.73320316829869.005748631
1062949.13683603829832.5729467041062821.23656033829707.022902776
#Sta/Elev= 30
9704.0488.5536889717.7519.7818699732.6679.1575399747.43210.545279806.79610.14358
9821.63711.134869840.41710.830169852.96213.006069865.945 13.19829904.23811.25562
9918.0839.5064159936.5349.3646619951.7736.0728079995.4353.85095210027.664.199805
10057.9611.9092210072.8812.3901710079.95 13.470510084.7515.1332110097.0521.51445
 10112.426.6019610162.1351.4995410175.4752.5260410189.0857.1750310203.5663.56314
10218.0568.8559510257.2881.92941 10271.184.6162410284.9286.1869410295.95 85.3717
#Mann= 3 , 0 , 0
9704.048    0.12       09704.048    0.12       010295.95    0.12       0
#XS Ineff= 2 , 0
       09868.149                       0
Bank Sta=9704.048,10295.95
Exp/Cntr=0.3,0.1

Type RM Length L Ch R = 1 ,368.8311,190.846200,190.846200,190.846200
XS GIS Cut Line= 2
1063292.38634804829912.1352302431063022.48062438829644.775786981
#Sta/Elev= 30
9817.5758.1165879827.972 8.264289841.9246.8947649856.1236.0988879870.1997.838385
9884.5537.0855269898.7627.2841849926.5018.3282679941.3917.3414879955.6016.966275
9968.7285.4843279982.8033.0164359996.8791.79664410012.441.85015610026.652.768904
10040.862.97193610055.072.77309510067.263.50817710083.49 8.6200810095.4111.07823
10109.4811.0170410111.9111.2253210123.5613.5839510137.6319.5561810151.7123.96758
10154.54  24.60210168.7526.4987110179.8628.6785410182.9629.0976610197.4829.95774
#Mann= 3 , 0 , 0
9817.575   0.055       09817.575   0.055       010197.48   0.055       0
#XS Ineff= 2 , 0
       09890.009                       0
Bank Sta=9817.575,10197.48
Exp/Cntr=0.3,0.1

Type RM Length L Ch R = 1 ,177.9849,177.984900,177.984900,177.984900
XS GIS Cut Line= 6
1063423.51978928830010.1670261321063356.04335839829763.177826121
1063331.85369447829702.0670962331063306.08208725829658.110032126
  1063229.998965 829568.404760541063098.88016966829409.185332313
#Sta/Elev= 30
9626.2816.2269999642.0035.894066 9652.374.4776259662.7364.9866139673.1034.322085
9693.8364.8793169724.9354.6999479735.3025.653833  9797.54.7194019891.1165.323965
9901.8716.0249969934.1364.8775149967.8290.43034510000.65 0.73552 10016.2-0.15546
10068.651.29198910081.762.91178510107.984.79453310124.498.90451910146.949.540763
10171.6811.9880710185.8116.9937510211.7220.4940410218.8722.1631810237.6326.86408
10263.5334.6809610289.4441.3318210297.53 44.264710315.3552.8875810322.8857.09344
#Mann= 3 , 0 , 0
9626.281  0.0605       09626.281  0.0605       010322.88  0.0605       0
#XS Ineff= 2 , 0
       09914.154        10131.42       0
Bank Sta=9626.281,10322.88
Exp/Cntr=0.3,0.1

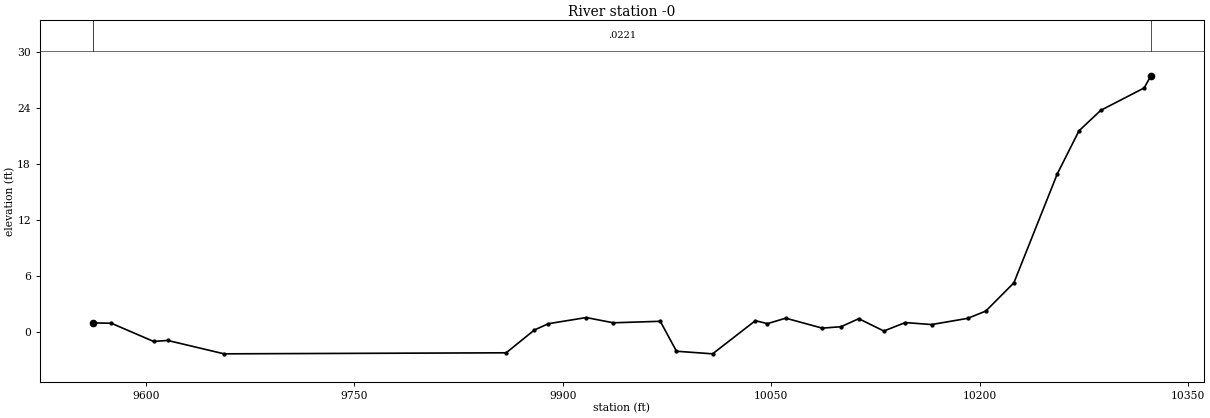
Type RM Length L Ch R = 1 ,      -0,0.000000,0.000000,0.000000
XS GIS Cut Line= 6
1063552.10695013829957.9682776781063494.81564084829626.951824054
1063449.99907187829552.4077253941063439.38837686829540.160595328
1063348.55114639829433.7522864041063231.85470012829293.707935721
#Sta/Elev= 30
9561.8790.946121 9575.040.9080899605.486-1.043489615.635-0.937979656.229-2.37368
9859.203-2.26264  9879.50.1826969889.6490.8595629916.8671.5175049936.2740.955119
9970.1031.1163949981.771-2.0952110007.76-2.3736810038.561.18342810047.23 0.86217
10060.381.45116210086.670.38146210100.170.53649910112.97 1.3937910130.980.074681
10146.450.98038510165.320.76614210191.351.43181610204.372.21352210224.56 5.23976
 10255.816.9227410271.42 21.539810287.0423.7314410318.2926.13508 10323.227.44137
#Mann= 3 , 0 , 0
9561.879  0.0221       09561.879  0.0221       0 10323.2  0.0221       0
#XS Ineff= 2 , 0
       09930.579        10068.33       0
Bank Sta=9561.879,10323.2
Exp/Cntr=0.3,0.1